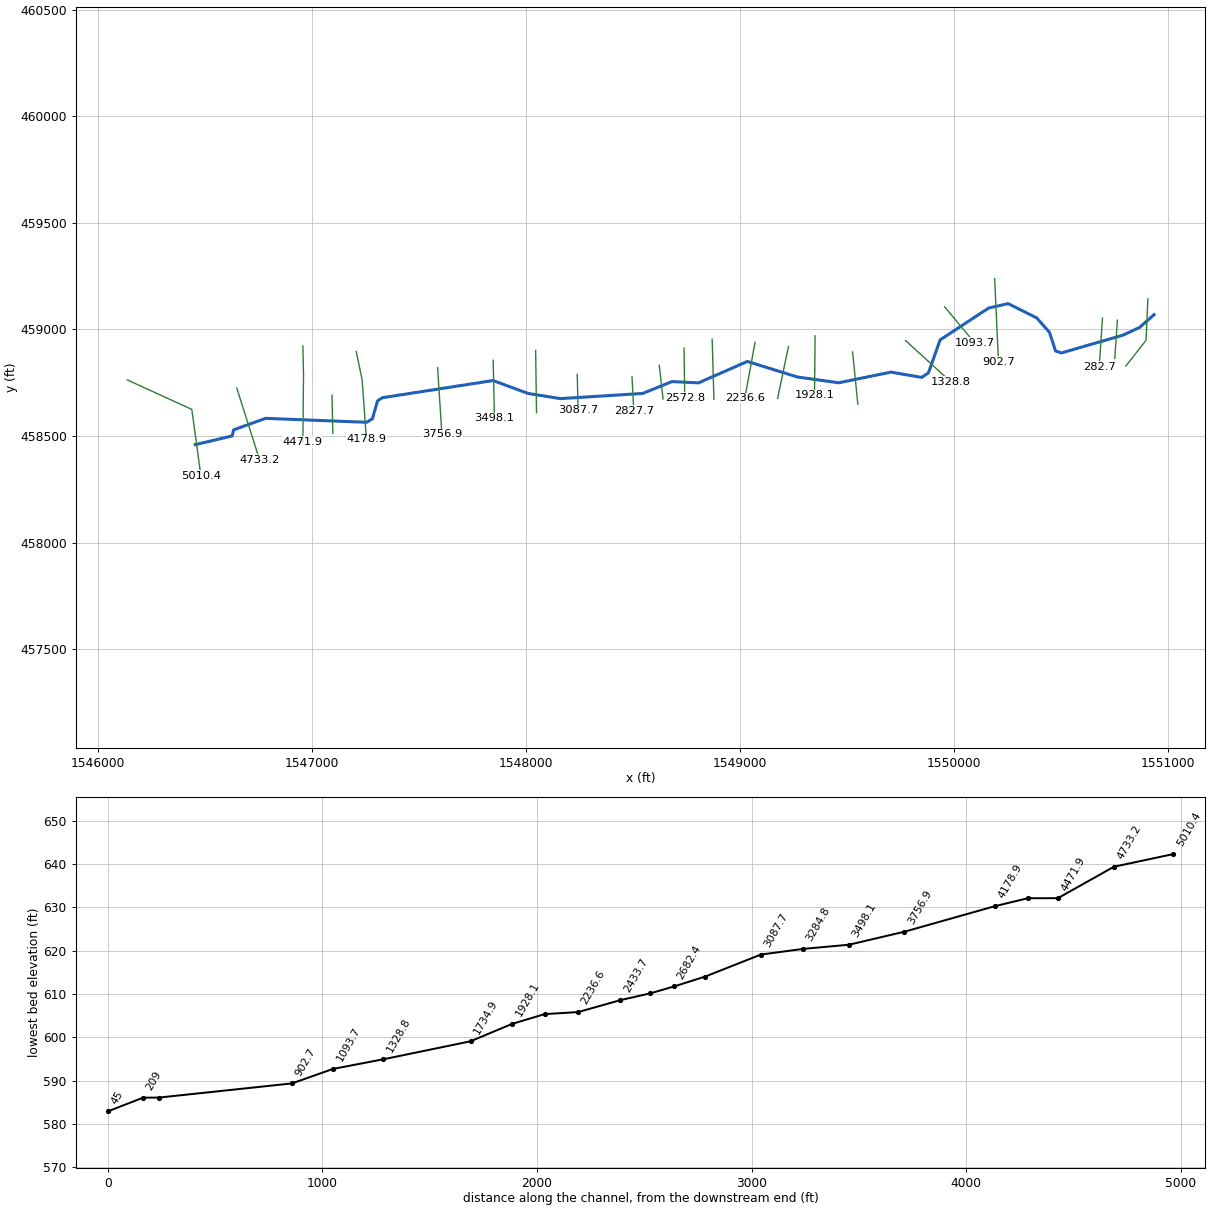
--- RFGARETCR.prj (project) ---

Proj Title=RFGARETCR
Current Plan=p01
Default Exp/Contr=0,0
English Units
Geom File=g01
Flow File=f01
Plan File=p01
BEGIN DESCRIPTION:
END DESCRIPTION:
DSS Export Rating Curves= 0
DSS Export Rating Curve Sorted= 0
DSS Export Volume Flow Curves= 0
DXF OffsetX= 0
DXF OffsetY= 0
DXF ScaleX= 0
DXF ScaleY= 0

--- RFGARETCR.p01 (plan) ---

Plan Title=Floodplain
Program Version=4.00
Geom File=g01
Flow File=f01
K Sum by GR=0
Std Step Tol=0.01
Critical Tol=0.01
Num of Std Step Trials=20
Max Error Tol=0.3
Flow Tol Ratio=0.001
Split Flow NTrial=30
Split Flow Tol=0.02
Split Flow Ratio=0.02
Log Output Level=0
Friction Slope Method=1
Unsteady Friction Slope Method=2
Unsteady Bridges Friction Slope Method=1
Global Log Level=0
CheckData=False
Run HTab=0
Run UNet=0
Run PostProcess=0
UNET Theta=0
UNET Theta Warmup=0
UNET ZTol=0
UNET ZSATol=0
UNET MxIter=0
UNET MaxInSteps=0
UNET DtIC=0
UNET DtMin=0
UNET MaxCRTS=0
UNET WFStab=0
UNET SFStab=0
UNET WFX=0
UNET SFX=0
UNET DSS MLevel=0
UNET DZMax Abort=0
UNET Convert EG Bridges=0
UNET Use Existing IB Tables=0
UNET Froude Limit=0
UNET Froude Power=0
Write IC File=0
Echo Input=False
Echo Output=False
Write Detailed=0

--- RFGARETCR.f01 (steady flow) ---

Flow Title=NFF Regression Equation
Program Version=4.00
Number of Profiles=1
Profile Names=P100yr
River Rch & RM=RFGARETCR,Main      ,5010.4
368.2489
River Rch & RM=RFGARETCR,Main      ,4471.9
381.3417
River Rch & RM=RFGARETCR,Main      ,2682.4
417.2420
River Rch & RM=RFGARETCR,Main      ,282.7
457.0572
Boundary for River Rch & Prof#=RFGARETCR,Main      ,1
Up Type=0
Dn Type=3
Dn Slope=0.007644

--- RFGARETCR.g01 (geometry) ---

Geom Title=Geometry
Program Version=4.00

River Reach=RFGARETCR       ,Main
Reach XY= 30
     1546454.219      458459.169     1546626.668      458500.224
     1546633.826      458528.856     1546782.967      458582.715
     1547254.397      458564.167     1547281.638      458580.304
     1547305.931      458664.974      1547329.04       458679.52
     1547845.264      458760.005      1548008.35       458699.77
     1548159.235      458675.159     1548543.957      458699.493
     1548681.228      458755.084     1548805.106        458749.1
     1549033.306      458849.536     1549266.672      458776.808
      1549459.83      458749.405     1549704.279      458799.528
     1549847.888      458774.618     1549879.426      458796.284
     1549933.557      458950.385     1550160.019      459099.883
     1550251.052      459120.859     1550384.945      459053.734
     1550444.311      458986.558     1550473.259      458898.554
     1550500.368       458889.58     1550786.831        458972.6
     1550865.103       459008.82     1550933.145       459068.93

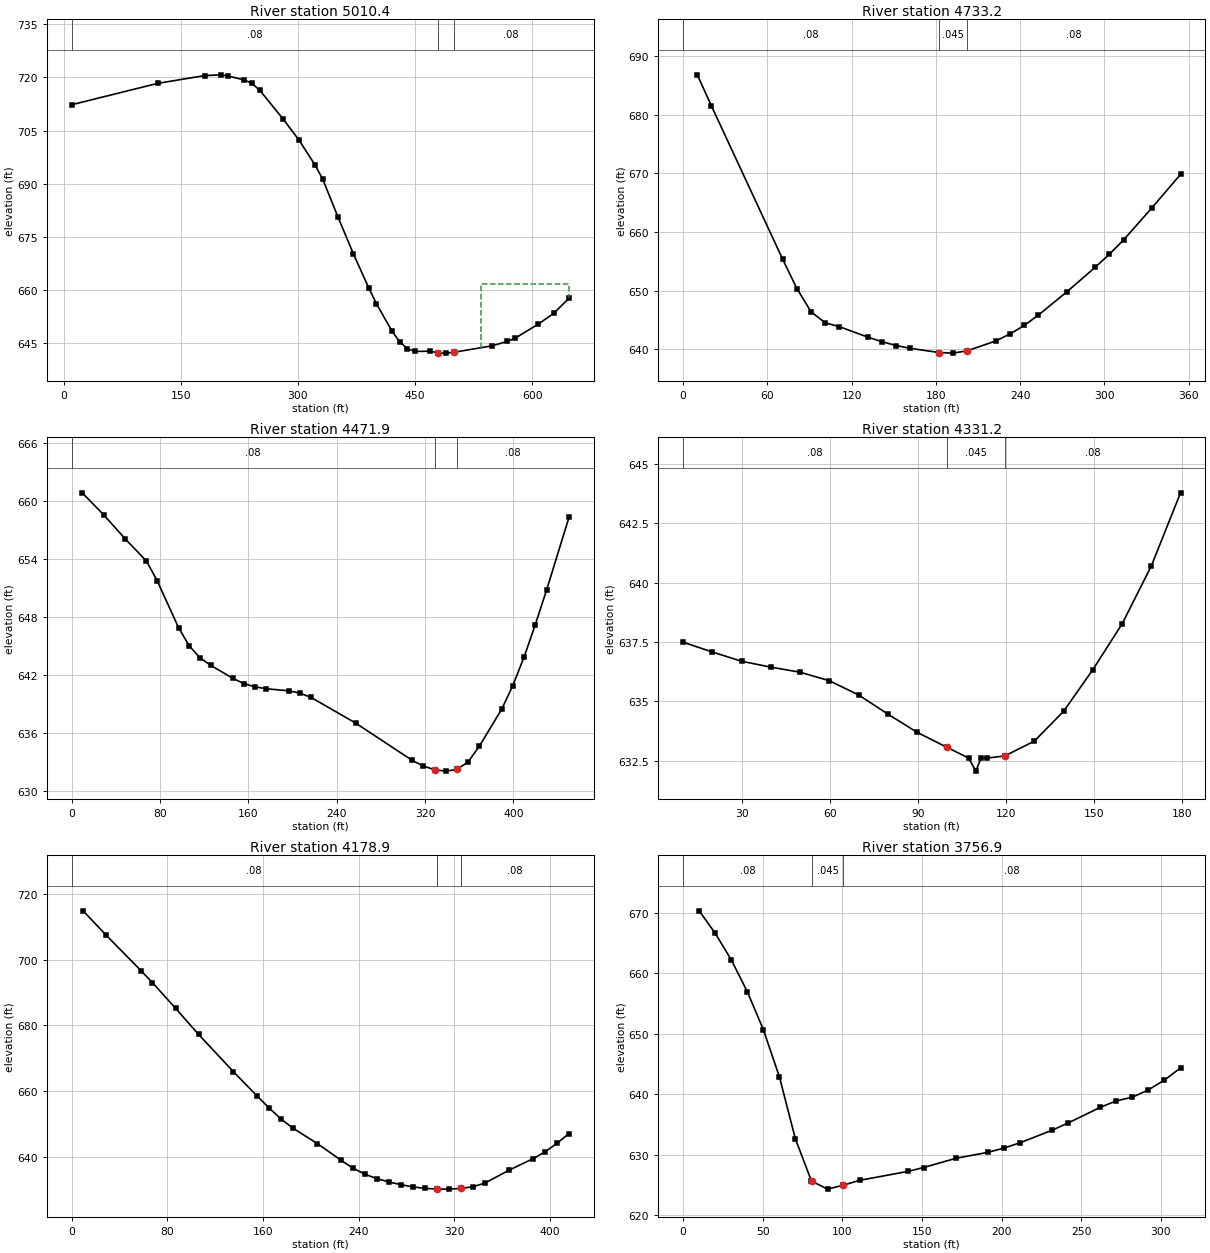
Type RM Length L Ch R = 1 ,5010.4  ,272.4,277.2,291.9
XS GIS Cut Line= 3
     1546136.784      458763.145     1546438.168      458624.605
     1546480.988      458312.018
#Sta/Elev= 30
    10.1  712.31   120.6  718.35   180.9  720.54     201  720.75   211.1  720.39
   231.2  719.32   241.2  718.32   251.3  716.37   281.4   708.2   301.5  702.34
   321.6  695.45   331.7  691.39   351.4  680.64   371.1  670.27   390.9   660.6
   400.7  656.15   420.4  648.54   430.3  645.51   440.2  643.52     450  642.75
   469.7  642.82   479.5  642.33   489.5  642.27   499.5   642.5   548.6  644.32
   568.3  645.58   578.2  646.49   607.8  650.43   627.5  653.45   647.2  657.74
#Mann= 3 , 0 , 0
    10.1     .08       0   479.5    .045       0   499.5     .08       0
#XS Ineff= 2 , 0
                           534.4          661.77
Permanent Ineff=
       F       F
Bank Sta=479.5,499.5
XS Rating Curve= 0 ,0
Exp/Cntr=0.3,0.1

Type RM Length L Ch R = 1 ,4733.2  ,269.2,261.2,253.3
XS GIS Cut Line= 2
      1546648.31      458724.898     1546755.098      458387.215
#Sta/Elev= 24
    10.1  686.76    20.2  681.44    70.8  655.39      81  650.35    91.1  646.38
   101.2  644.51   111.3  643.86   131.5  642.07   141.7  641.29   151.8  640.64
   161.9  640.16   182.3  639.45   192.3  639.35   202.3  639.75   222.6  641.42
   232.7  642.61   242.9  644.06     253  645.84   273.2  649.78   293.5  653.99
   303.6  656.21   313.7  658.65   333.9  664.13   354.2   669.8
#Mann= 3 , 0 , 0
       0     .08       0   182.3    .045       0   202.3     .08       0
Bank Sta=182.3,202.3
XS Rating Curve= 0 ,0
Exp/Cntr=0.3,0.1

Type RM Length L Ch R = 1 ,4471.9  ,140,140.8,141.5
XS GIS Cut Line= 3
     1546957.208      458922.173     1546960.094      458786.522
     1546957.208      458471.929
#Sta/Elev= 30
     9.7  660.81    29.1  658.54    48.5  656.07    67.8  653.77    77.5  651.75
    96.9  646.89   106.6  645.01   116.3  643.78     126  643.01   145.8  641.68
     156  641.12   166.1  640.79   176.3  640.59   196.6  640.38   206.7  640.14
   216.9  639.69   257.5  637.03   308.2  633.21   318.4  632.62   328.7  632.23
   338.7  632.09   348.7  632.26     359  633.03   369.1  634.65   389.4  638.48
   399.5  640.92   409.7  643.87   419.8   647.2     430  650.76   450.3  658.27
#Mann= 3 , 0 , 0
       0     .08       0   328.7    .045       0   348.7     .08       0
Bank Sta=328.7,348.7
XS Rating Curve= 0 ,0
Exp/Cntr=0.3,0.1

Type RM Length L Ch R = 1 ,4331.2  ,151,152.2,153.5
XS GIS Cut Line= 2
      1547093.25      458691.278     1547097.007      458511.883
#Sta/Elev= 22
      10  637.49    19.9  637.08    29.9  636.69    39.9  636.44    49.8  636.23
    59.8  635.87    69.8  635.27    79.7  634.47    89.7   633.7    99.7  633.08
  107.21  632.62   109.7  632.07  111.44  632.62  113.56  632.62   119.6  632.71
   119.7  632.72   129.6  633.33   139.6  634.59   149.5  636.33   159.5  638.26
   169.5  640.71   179.4  643.77
#Mann= 3 , 0 , 0
      10     .08       0    99.7    .045       0   119.7     .08       0
Bank Sta=99.7,119.7
XS Rating Curve= 0 ,0
Exp/Cntr=0.3,0.1

Type RM Length L Ch R = 1 ,4178.9  ,423.1,422,420.9
XS GIS Cut Line= 3
     1547206.509      458896.272     1547233.714      458763.691
     1547253.996      458483.796
#Sta/Elev= 30
     9.7   714.8      29  707.38      58  696.66    67.7  692.98      87  685.19
   106.3  677.23   135.3  665.96   155.4  658.46   165.4  654.84   175.4  651.49
   185.5   648.7   205.5  644.11   225.5  638.98   235.6  636.59   245.6  634.73
   255.6  633.42   265.6  632.41   275.7  631.57   285.7  630.92   295.7  630.49
   305.7  630.27   315.7  630.25   325.7  630.47   335.8  630.98   345.8   632.1
   365.9     636   385.9  639.49   395.9  641.54     406  644.17     416  647.14
#Mann= 3 , 0 , 0
       0     .08       0   305.7    .045       0   325.7     .08       0
Bank Sta=305.7,325.7
XS Rating Curve= 0 ,0
Exp/Cntr=0.3,0.1

Type RM Length L Ch R = 1 ,3756.9  ,259.9,258.8,257.7
XS GIS Cut Line= 2
     1547586.319      458820.142     1547606.522      458508.435
#Sta/Elev= 26
    10.1  670.29    20.2  666.57    30.2  662.22    40.3  656.95    50.4  650.67
    60.5  642.86    70.5  632.64    80.6  625.68    80.7  625.67    90.7  624.35
   100.7  625.01   110.8   625.8   141.1  627.27   151.1  627.92   171.3  629.44
   191.4  630.42   201.5  631.13   211.6     632   231.8  634.08   241.8  635.27
     262  637.85   272.1  638.92   282.1  639.52   292.2  640.73   302.3  642.35
   312.4  644.36
#Mann= 3 , 0 , 0
       0     .08       0    80.7    .045       0   100.7     .08       0
Bank Sta=80.7,100.7
XS Rating Curve= 0 ,0
Exp/Cntr=0.3,0.1

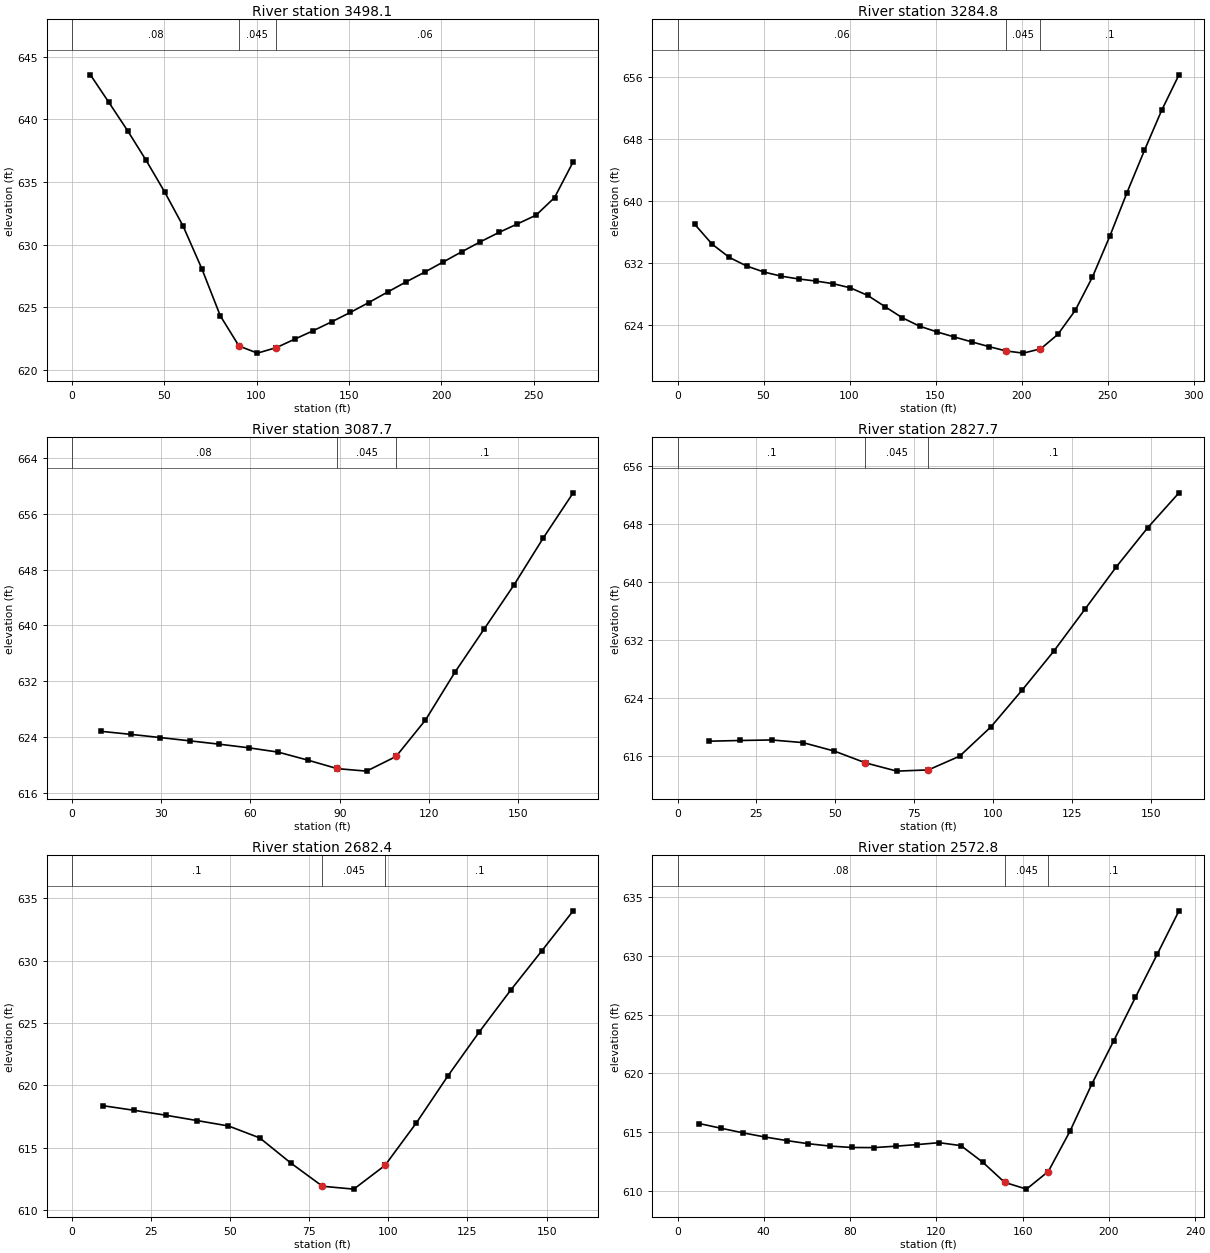
Type RM Length L Ch R = 1 ,3498.1  ,213.4,213.3,213.1
XS GIS Cut Line= 2
     1547846.075      458854.777     1547851.847      458583.476
#Sta/Elev= 28
    10.1  643.55    20.1  641.35    30.2   639.1    40.2  636.74    50.3   634.2
    60.3  631.47    70.4  628.08    80.4  624.32    90.5  621.91   100.5  621.34
   110.5  621.77   110.6  621.77   120.6  622.45   130.7  623.13   140.7  623.84
   150.8  624.59   160.8  625.38   170.9  626.21   180.9  627.02     191   627.8
     201  628.61   211.1  629.43   221.1  630.22   231.2  630.97   241.2  631.65
   251.3  632.35   261.3  633.75   271.4  636.61
#Mann= 3 , 0 , 0
       0     .08       0    90.5    .045       0   110.5     .06       0
Bank Sta=90.5,110.5
XS Rating Curve= 0 ,0
Exp/Cntr=0.3,0.1

Type RM Length L Ch R = 1 ,3284.8  ,196.8,197.2,197.5
XS GIS Cut Line= 2
     1548044.332      458900.839     1548048.437      458609.387
#Sta/Elev= 30
    10.1  636.98    20.1  634.44    30.2  632.72    40.2  631.62    50.3  630.84
    60.3  630.31    70.4  629.95    80.4  629.68    90.5  629.34   100.5   628.8
   110.6  627.82   120.6  626.38   130.7  624.94   140.7  623.86   150.8  623.12
   160.8  622.47   170.9  621.84   180.9  621.23     191  620.66     201  620.38
     211  620.93   211.1  620.93   221.1   622.8   231.2   625.9   241.2   630.2
   251.3  635.47   261.3   641.1   271.4  646.53   281.4  651.69   291.5  656.29
#Mann= 3 , 0 , 0
       0     .06       0     191    .045       0     211      .1       0
Bank Sta=191,211
XS Rating Curve= 0 ,0
Exp/Cntr=0.3,0.1

Type RM Length L Ch R = 1 ,3087.7  ,259.2,259.9,260.7
XS GIS Cut Line= 2
     1548238.633      458788.637     1548242.738      458620.334
#Sta/Elev= 19
     9.9  624.78    19.8  624.35    29.7  623.89    39.6  623.42    49.5  622.94
    59.4  622.42    69.3   621.8    79.2  620.66      89  619.45    89.1  619.43
      99  619.07   108.9  621.17     109  621.22   118.8  626.41   128.7  633.28
   138.6  639.53   148.5  645.78   158.4  652.57   168.4  659.02
#Mann= 3 , 0 , 0
       0     .08       0      89    .045       0     109      .1       0
Bank Sta=89,109
XS Rating Curve= 0 ,0
Exp/Cntr=0.3,0.1

Type RM Length L Ch R = 1 ,2827.7  ,143.8,145.4,146.9
XS GIS Cut Line= 2
     1548494.508       458777.69     1548502.718      458618.966
#Sta/Elev= 17
     9.9   618.1    19.9   618.2    29.8  618.27    39.7  617.91    49.7  616.74
    59.5  615.13    59.6  615.11    69.5  613.98    79.5  614.15    89.4  616.04
    99.3  620.07   109.3  625.19   119.2  630.48   129.1  636.27   139.1  642.14
     149   647.5   158.9   652.3
#Mann= 3 , 0 , 0
       0      .1       0    59.5    .045       0    79.5      .1       0
Bank Sta=59.5,79.5
XS Rating Curve= 0 ,0
Exp/Cntr=0.3,0.1

Type RM Length L Ch R = 1 ,2682.4  ,112,109.6,107.1
XS GIS Cut Line= 2
     1548621.761      458831.055     1548639.549      458673.698
#Sta/Elev= 18
     9.9  618.38    19.8  618.01    29.7  617.62    39.6  617.19    49.5  616.76
    59.4   615.8    69.3  613.77    79.1  611.95    79.2  611.93    89.1   611.7
      99  613.61    99.1  613.65   108.9  617.02   118.8  620.76   128.7  624.28
   138.6  627.62   148.5  630.79   158.4  633.99
#Mann= 3 , 0 , 0
       0      .1       0    79.1    .045       0    99.1      .1       0
Bank Sta=79.1,99.1
XS Rating Curve= 0 ,0
Exp/Cntr=0.3,0.1

Type RM Length L Ch R = 1 ,2572.8  ,139.3,139.1,139
XS GIS Cut Line= 2
     1548737.605      458912.044     1548740.688       458679.52
#Sta/Elev= 25
    10.1  615.71    20.2  615.31    30.3  614.92    40.4  614.57    50.6  614.26
    60.7  613.99    70.8  613.79    80.9  613.67      91  613.66   101.1  613.78
   111.2  613.92   121.3  614.08   131.4  613.83   141.5  612.42   151.7  610.69
   151.8  610.69   161.8  610.12   171.8  611.61   171.9  611.62     182  615.07
   192.1  619.08   202.2  622.75   212.3  626.47   222.4  630.14   232.5  633.85
#Mann= 3 , 0 , 0
       0     .08       0   151.8    .045       0   171.8      .1       0
Bank Sta=151.8,171.8
XS Rating Curve= 0 ,0
Exp/Cntr=0.3,0.1

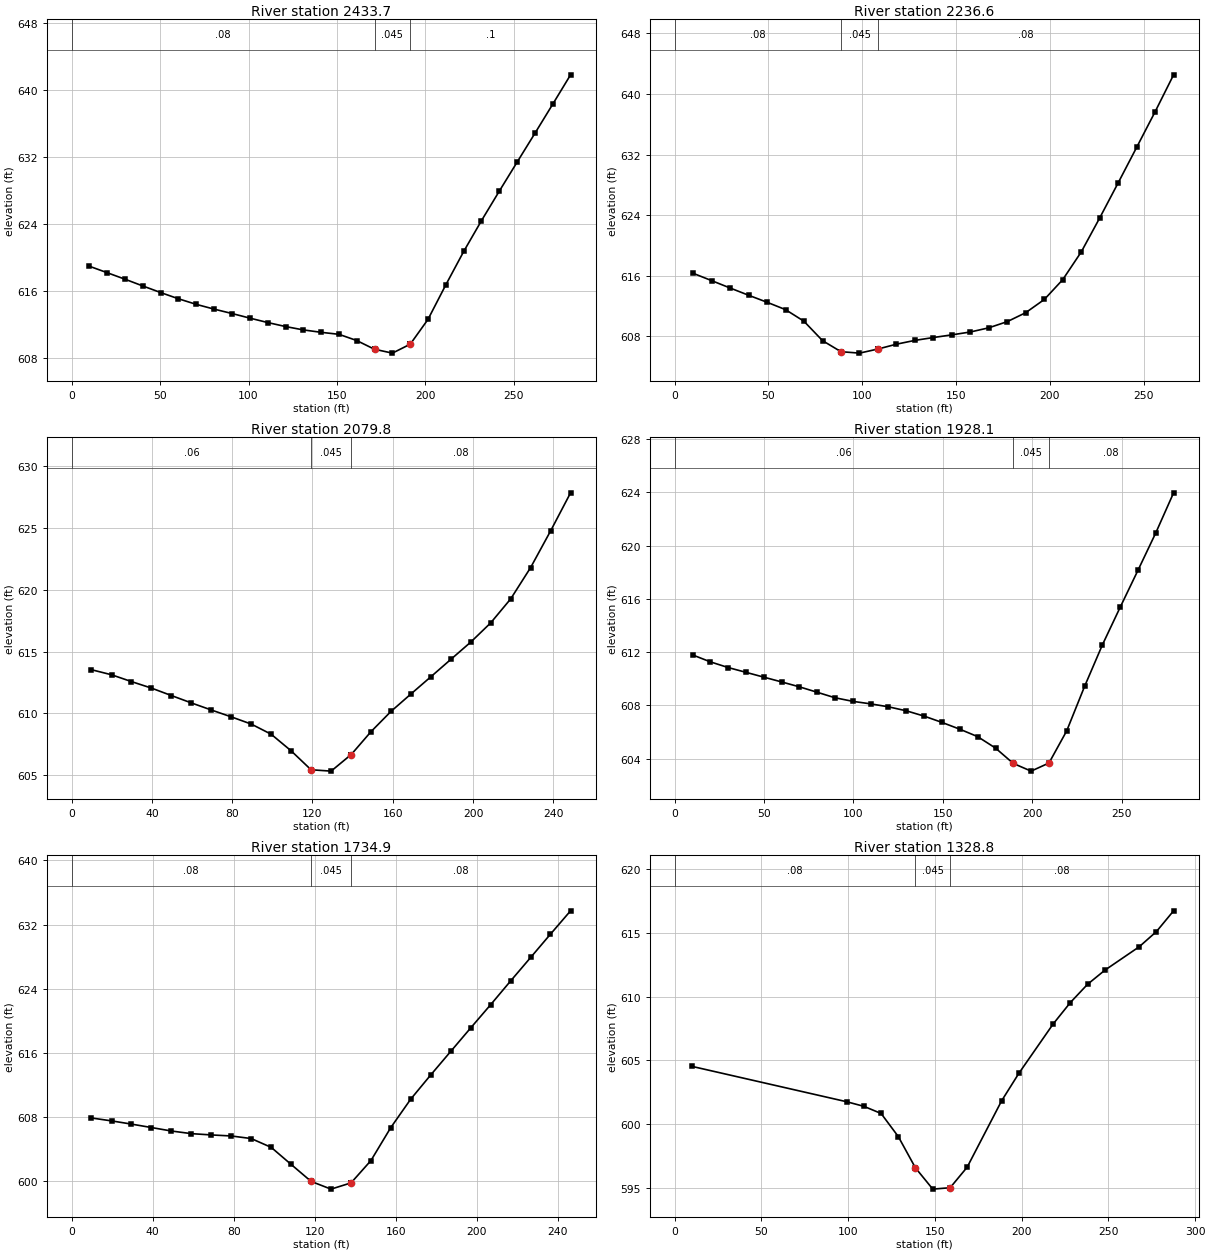
Type RM Length L Ch R = 1 ,2433.7  ,201.9,197.1,192.3
XS GIS Cut Line= 2
     1548868.956      458953.592     1548877.166      458671.719
#Sta/Elev= 30
    10.1  618.95    20.1  618.18    30.2   617.4    40.3  616.59    50.4   615.8
    60.4  615.06    70.5  614.39    80.6  613.82    90.6   613.3   100.7  612.75
   110.8  612.22   120.9  611.74   130.9  611.34     141  611.05   151.1  610.81
   161.1  610.07   171.2  609.02   171.3  609.02   181.3  608.56   191.3  609.62
   191.4  609.63   201.4  612.59   211.5  616.73   221.6  620.72   231.6  624.39
   241.7  627.93   251.8  631.41   261.9  634.87   271.9  638.33     282  641.85
#Mann= 3 , 0 , 0
       0     .08       0   171.3    .045       0   191.3      .1       0
Bank Sta=171.3,191.3
XS Rating Curve= 0 ,0
Exp/Cntr=0.3,0.1

Type RM Length L Ch R = 1 ,2236.6  ,157.4,156.8,156.2
XS GIS Cut Line= 2
     1549069.261      458939.133     1549021.598      458677.492
#Sta/Elev= 29
     9.8  616.34    19.7  615.37    29.5   614.4    39.4  613.44    49.2  612.52
    59.1  611.54    68.9  610.01    78.8  607.45    88.5  606.01    88.6  605.99
    98.5   605.8   108.3  606.34   108.5  606.35   118.2  606.98     128  607.48
   137.9  607.86   147.7  608.21   157.6  608.59   167.4  609.14   177.3  609.96
   187.1  611.14     197  612.88   206.8  615.49   216.7  619.16   226.5  623.63
   236.4  628.29   246.2  632.95   256.1  637.68   265.9  642.53
#Mann= 3 , 0 , 0
       0     .08       0    88.5    .045       0   108.5     .08       0
Bank Sta=88.5,108.5
XS Rating Curve= 0 ,0
Exp/Cntr=0.3,0.1

Type RM Length L Ch R = 1 ,2079.8  ,146.8,151.7,156.6
XS GIS Cut Line= 2
     1549225.435      458919.865     1549174.729      458676.477
#Sta/Elev= 26
     9.9  613.53    19.9  613.12    29.8  612.57    39.8  612.04    49.7  611.44
    59.7  610.84    69.6  610.27    79.6  609.71    89.5  609.13    99.4  608.31
   109.4  606.96   119.3  605.43   129.3  605.32   139.2  606.65   139.3  606.66
   149.2  608.52   159.1  610.15   169.1  611.57     179  612.96   188.9  614.36
   198.9  615.77   208.8  617.32   218.8  619.27   228.7   621.8   238.7  624.78
   248.6  627.85
#Mann= 3 , 0 , 0
       0     .06       0   119.3    .045       0   139.3     .08       0
Bank Sta=119.3,139.3
XS Rating Curve= 0 ,0
Exp/Cntr=0.3,0.1

Type RM Length L Ch R = 1 ,1928.1  ,190.3,193.2,196
XS GIS Cut Line= 2
     1549349.705      458969.254     1549346.968      458690.118
#Sta/Elev= 28
      10  611.79    19.9  611.27    29.9  610.84    39.9  610.48    49.8  610.12
    59.8  609.76    69.8  609.39    79.8  608.98    89.7  608.57    99.7   608.3
   109.7  608.11   119.6  607.89   129.6  607.59   139.6  607.19   149.5  606.72
   159.5  606.21   169.5  605.65   179.5  604.79   189.4  603.64   199.4  603.06
   209.4  603.67   219.3  606.08   229.3  609.42   239.3  612.55   249.2  615.36
   259.2  618.15   269.2  620.97   279.1  623.96
#Mann= 3 , 0 , 0
       0     .06       0   189.4    .045       0   209.4     .08       0
Bank Sta=189.4,209.4
XS Rating Curve= 0 ,0
Exp/Cntr=0.3,0.1

Type RM Length L Ch R = 1 ,1734.9  ,386.5,406.1,424.7
XS GIS Cut Line= 2
     1549524.849      458893.997     1549549.479      458649.069
#Sta/Elev= 27
     9.8  607.91    19.7  607.55    29.5  607.15    39.4  606.72    49.2  606.29
    59.1  605.96    68.9   605.8    78.8  605.67    88.6  605.35    98.5  604.25
   108.3  602.13     118  600.05   118.2  600.01     128  599.05   137.9  599.83
     138  599.86   147.7  602.61   157.5  606.72   167.4  610.28   177.2  613.27
   187.1  616.21   196.9  619.12   206.8  622.03   216.6  624.97   226.5   627.9
   236.3  630.81   246.2  633.71
#Mann= 3 , 0 , 0
       0     .08       0     118    .045       0     138     .08       0
Bank Sta=118,138
XS Rating Curve= 0 ,0
Exp/Cntr=0.3,0.1

Type RM Length L Ch R = 1 ,1328.8  ,238.5,235,231.9
XS GIS Cut Line= 2
     1549772.514      458947.361     1549984.603      458753.061
#Sta/Elev= 18
     9.9  604.54    99.2  601.76   109.1   601.4     119  600.84   128.9  599.03
   138.8  596.57   148.8   594.9   158.8  595.01   168.6  596.62   188.5  601.84
   198.4  603.99   218.2  607.87   228.1  609.55     238  610.98     248  612.09
   267.8  613.93   277.7  615.12   287.6  616.75
#Mann= 3 , 0 , 0
       0     .08       0   138.8    .045       0   158.8     .08       0
Bank Sta=138.8,158.8
XS Rating Curve= 0 ,0
Exp/Cntr=0.3,0.1

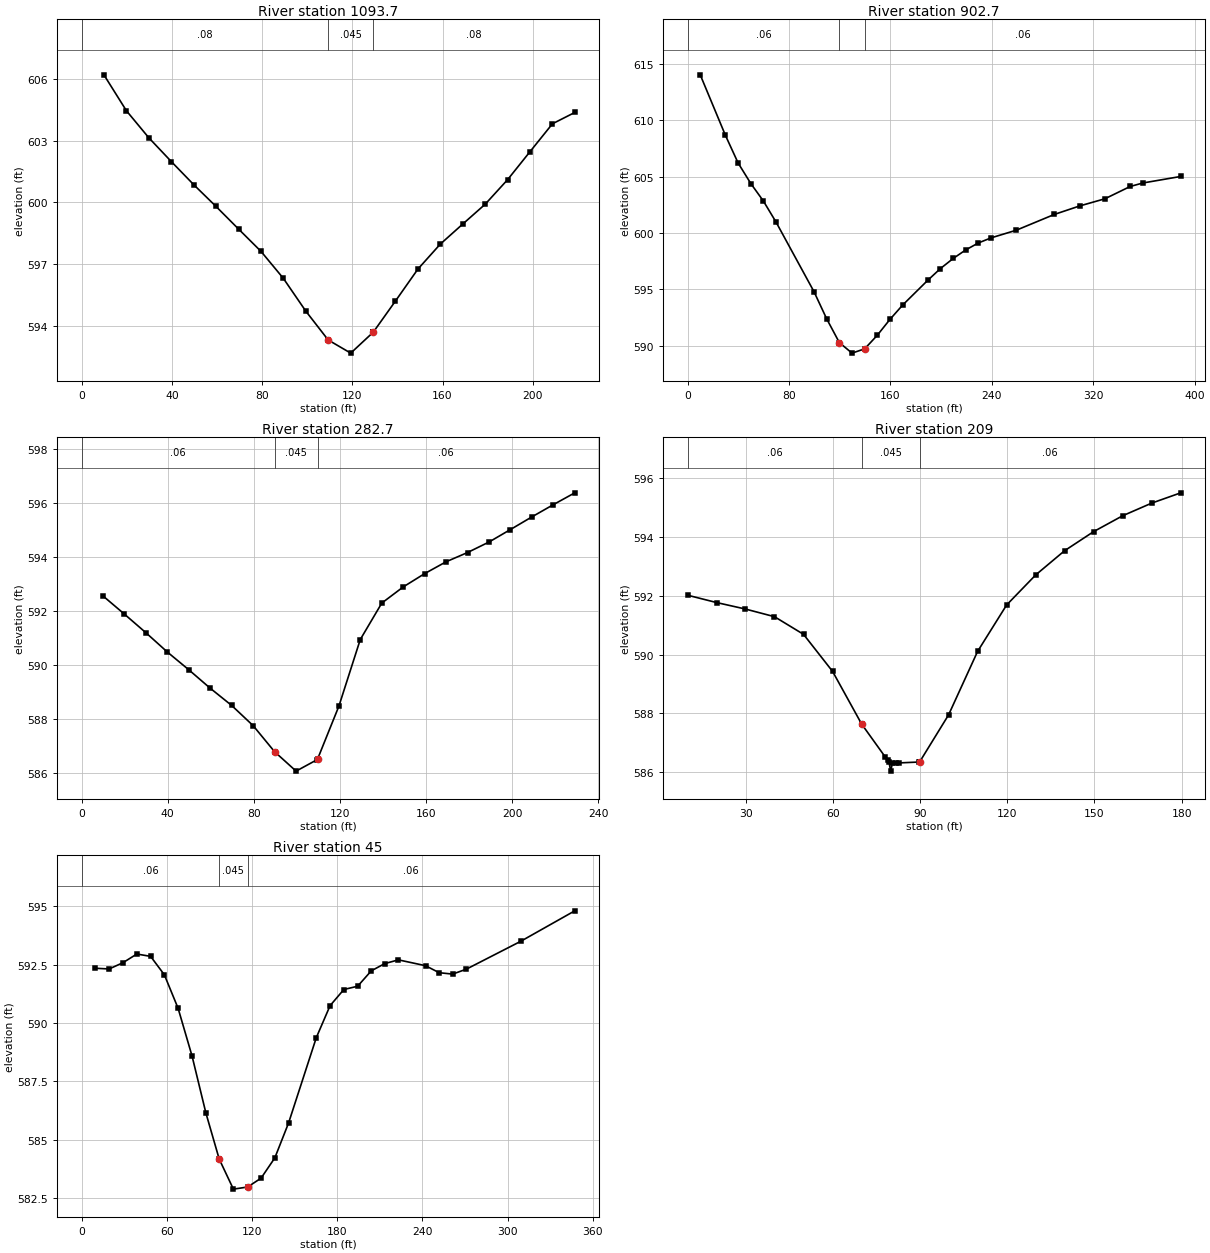
Type RM Length L Ch R = 1 ,1093.7  ,207.4,191,174.6
XS GIS Cut Line= 2
       1549954.5      459106.086     1550094.068      458937.783
#Sta/Elev= 23
     9.9   606.2    19.9  604.45    29.8  603.14    39.8  601.98    49.7  600.86
    59.6   599.8    69.6   598.7    79.5  597.62    89.4  596.31    99.4  594.71
   109.3  593.31   119.3  592.67   129.2  593.68   129.3  593.69   139.1   595.2
   149.1  596.76     159  597.97     169  598.95   178.9  599.91   188.8   601.1
   198.8  602.47   208.7  603.82   218.6  604.37
#Mann= 3 , 0 , 0
       0     .08       0   109.3    .045       0   129.3     .08       0
Bank Sta=109.3,129.3
XS Rating Curve= 0 ,0
Exp/Cntr=0.3,0.1

Type RM Length L Ch R = 1 ,902.7   ,623.1,620,617
XS GIS Cut Line= 2
     1550188.482      459237.444      1550206.27      458848.843
#Sta/Elev= 27
      10  614.03    29.9  608.65    39.9   606.2    49.9  604.38    59.8  602.83
    69.8  600.96    99.7  594.79   109.7  592.38   119.7  590.27   129.7  589.33
   139.7  589.71   149.6  590.91   159.6  592.32   169.6  593.59   189.5   595.8
   199.5  596.84   209.5  597.73   219.4  598.49   229.4  599.11   239.4  599.56
   259.3  600.24   289.3  601.64   309.2  602.39   329.2  603.03   349.1  604.12
   359.1  604.43     389  605.01
#Mann= 3 , 0 , 0
       0     .06       0   119.7    .045       0   139.7     .06       0
Bank Sta=119.7,139.7
XS Rating Curve= 0 ,0
Exp/Cntr=0.3,0.1

Type RM Length L Ch R = 1 ,282.7   ,74.2,73.7,73
XS GIS Cut Line= 2
     1550692.022      459052.722      1550676.97      458824.213
#Sta/Elev= 24
      10  592.54    19.9  591.87    29.9  591.18    39.8  590.47    49.8  589.81
    59.7  589.13    69.7  588.49    79.7  587.74    89.6  586.78    99.6  586.06
   109.5  586.49   109.6  586.51   119.5  588.47   129.4  590.93   139.4  592.28
   149.4  592.88   159.3  593.37   169.3  593.81   179.2  594.15   189.2  594.54
   199.1     595   209.1  595.47     219  595.92     229  596.36
#Mann= 3 , 0 , 0
       0     .06       0    89.6    .045       0   109.6     .06       0
Bank Sta=89.6,109.6
XS Rating Curve= 0 ,0
Exp/Cntr=0.3,0.1

Type RM Length L Ch R = 1 ,209     ,167.7,164,160.5
XS GIS Cut Line= 2
     1550761.806      459043.143     1550749.491      458863.894
#Sta/Elev= 25
      10  592.02      20  591.77    29.9  591.55    39.9  591.29    49.9  590.69
    59.9  589.43    69.9  587.64    78.1  586.51   78.82  586.41   79.32  586.34
    79.9  586.04   80.48  586.31   81.55  586.31   82.92  586.32    89.8  586.35
    89.9  586.36    99.8  587.95   109.8  590.11   119.8  591.69   129.8  592.71
   139.7  593.53   149.7  594.18   159.7  594.72   169.7  595.15   179.7   595.5
#Mann= 3 , 0 , 0
      10     .06       0    69.9    .045       0    89.9     .06       0
Bank Sta=69.9,89.9
XS Rating Curve= 0 ,0
Exp/Cntr=0.3,0.1

Type RM Length L Ch R = 1 ,45      ,20.6,45,69.4
XS GIS Cut Line= 3
     1550904.111       459143.03     1550895.666      458948.799
     1550801.487      458828.318
#Sta/Elev= 28
     9.7  592.34    19.4  592.31    29.2  592.58    38.9  592.95    48.6  592.85
    58.3  592.06      68  590.62    77.8  588.58    87.5  586.15    96.9  584.17
   106.9  582.88   116.9  582.97   126.4  583.35   136.1  584.22   145.8  585.72
   165.3  589.37     175  590.74   184.7  591.43   194.4  591.57     204  592.23
   213.5  592.54   223.1   592.7   242.2  592.45   251.8  592.15   261.3  592.09
   270.9   592.3   309.1  593.49   347.3   594.8
#Mann= 3 , 0 , 0
       0     .06       0    96.9    .045       0   116.9     .06       0
Bank Sta=96.9,116.9
XS Rating Curve= 0 ,0
Exp/Cntr=0.3,0.1

Chan Stop Cuts=-1
Use User Specified Reach Order=0